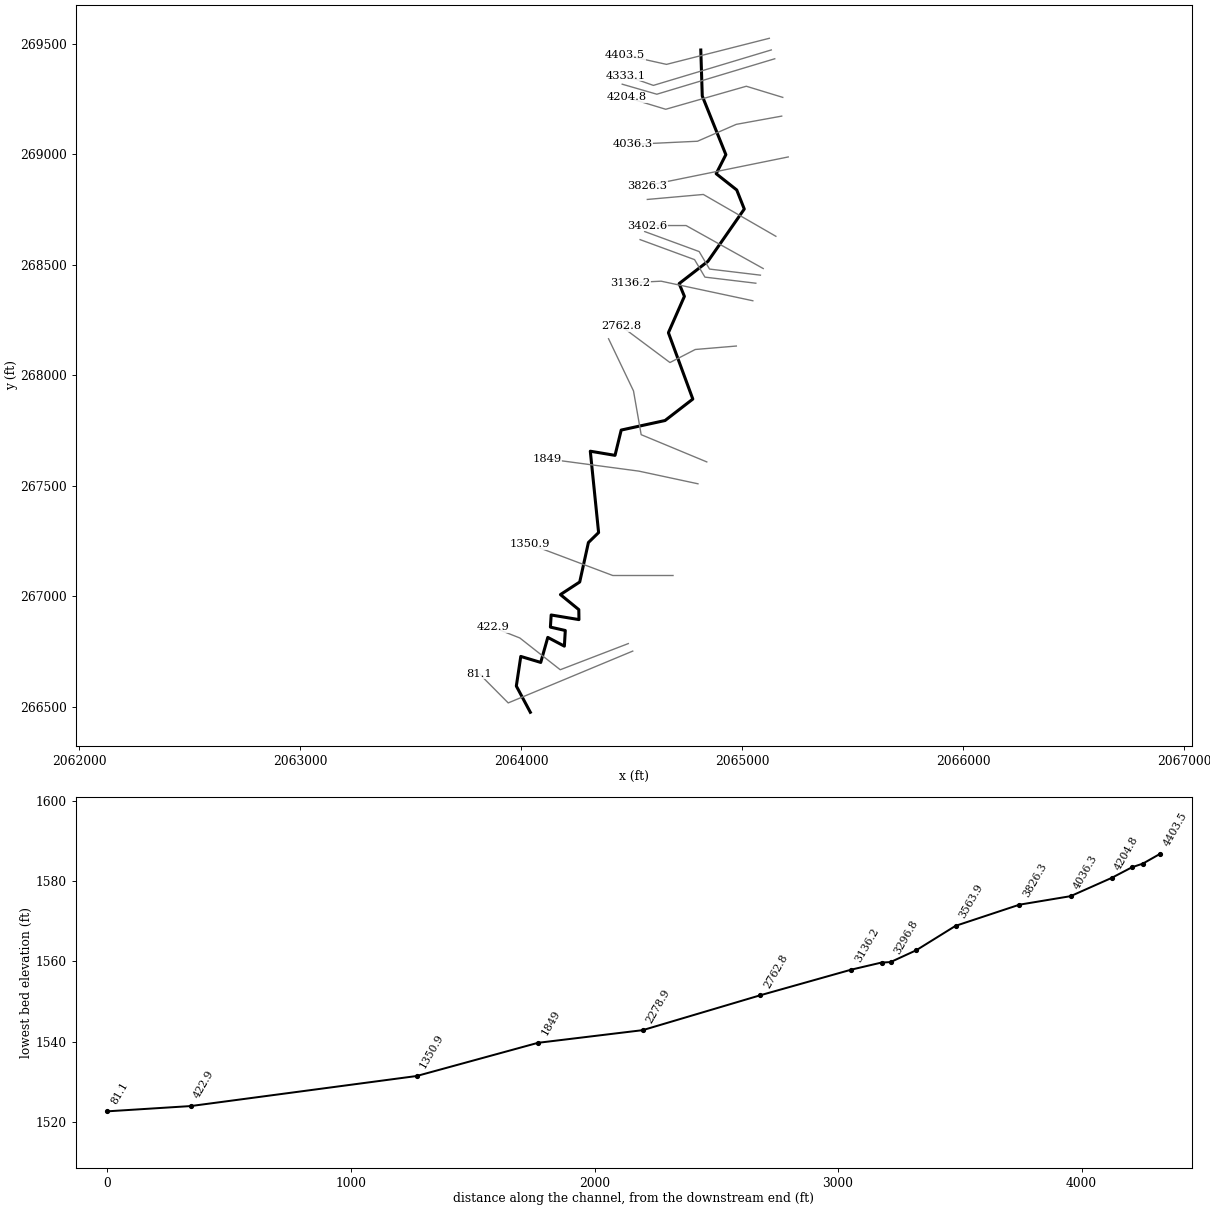
--- GRNBRTRIB2.prj (project) ---

Proj Title=GRNBRTRIB2
Current Plan=p01
Default Exp/Contr=0,0
English Units
Geom File=g01
Flow File=f01
Plan File=p01
BEGIN DESCRIPTION:
END DESCRIPTION:
DSS Export Rating Curves= 0
DSS Export Rating Curve Sorted= 0
DSS Export Volume Flow Curves= 0
DXF OffsetX= 0
DXF OffsetY= 0
DXF ScaleX= 0
DXF ScaleY= 0

--- GRNBRTRIB2.p01 (plan) ---

Plan Title=Floodplain
Program Version=4.00
Geom File=g01
Flow File=f01
K Sum by GR=0
Std Step Tol=0.01
Critical Tol=0.01
Num of Std Step Trials=20
Max Error Tol=0.3
Flow Tol Ratio=0.001
Split Flow NTrial=30
Split Flow Tol=0.02
Split Flow Ratio=0.02
Log Output Level=0
Friction Slope Method=1
Unsteady Friction Slope Method=2
Unsteady Bridges Friction Slope Method=1
Global Log Level=0
CheckData=False
Run HTab=0
Run UNet=0
Run PostProcess=0
UNET Theta=0
UNET Theta Warmup=0
UNET ZTol=0
UNET ZSATol=0
UNET MxIter=0
UNET MaxInSteps=0
UNET DtIC=0
UNET DtMin=0
UNET MaxCRTS=0
UNET WFStab=0
UNET SFStab=0
UNET WFX=0
UNET SFX=0
UNET DSS MLevel=0
UNET DZMax Abort=0
UNET Convert EG Bridges=0
UNET Use Existing IB Tables=0
UNET Froude Limit=0
UNET Froude Power=0
Write IC File=0
Echo Input=False
Echo Output=False
Write Detailed=0

--- GRNBRTRIB2.f01 (steady flow) ---

Flow Title=2010 USGS WV Regression Equation
Program Version=5.03
Number of Profiles= 1
Profile Names=P100yr
River Rch & RM=GRNBRTRIB2,Main            ,4403.5
553.0311
River Rch & RM=GRNBRTRIB2,Main            ,422.9
591.0858
River Rch & RM=GRNBRTRIB2,Main            ,81.1
 591.588
Boundary for River Rch & Prof#=GRNBRTRIB2,Main            , 1
Up Type= 0
Dn Type= 3
Dn Slope=0.00377
DSS Import GetInterval= 0
DSS Import GetPeak= 0
DSS Import FillOption= 0

--- GRNBRTRIB2.g01 (geometry) ---

Geom Title=LiDAR
Program Version=5.03

River Reach=GRNBRTRIB2      ,Main
Reach XY= 30
     2064812.544      269471.616     2064819.232      269263.547
     2064925.965      268998.214     2064882.142      268912.022
     2064975.197      268838.411     2065009.299      268752.121
     2064844.802      268515.575     2064714.594      268414.881
     2064738.392      268357.161     2064666.011      268192.654
     2064776.457      267892.447     2064650.892      267795.356
     2064452.493      267752.169     2064424.503      267637.717
     2064312.697      267656.467     2064350.197      267288.411
     2064304.075      267243.339     2064264.781        267064.8
     2064177.511      267007.814     2064260.614        266939.8
     2064261.308      266894.661     2064135.614      266915.494
     2064132.142      266860.633     2064199.503      266845.356
     2064195.336      266774.522     2064120.336      266814.106
     2064088.392      266700.911     2063998.114      266727.994
     2063977.975      266593.967     2064041.338      266475.345

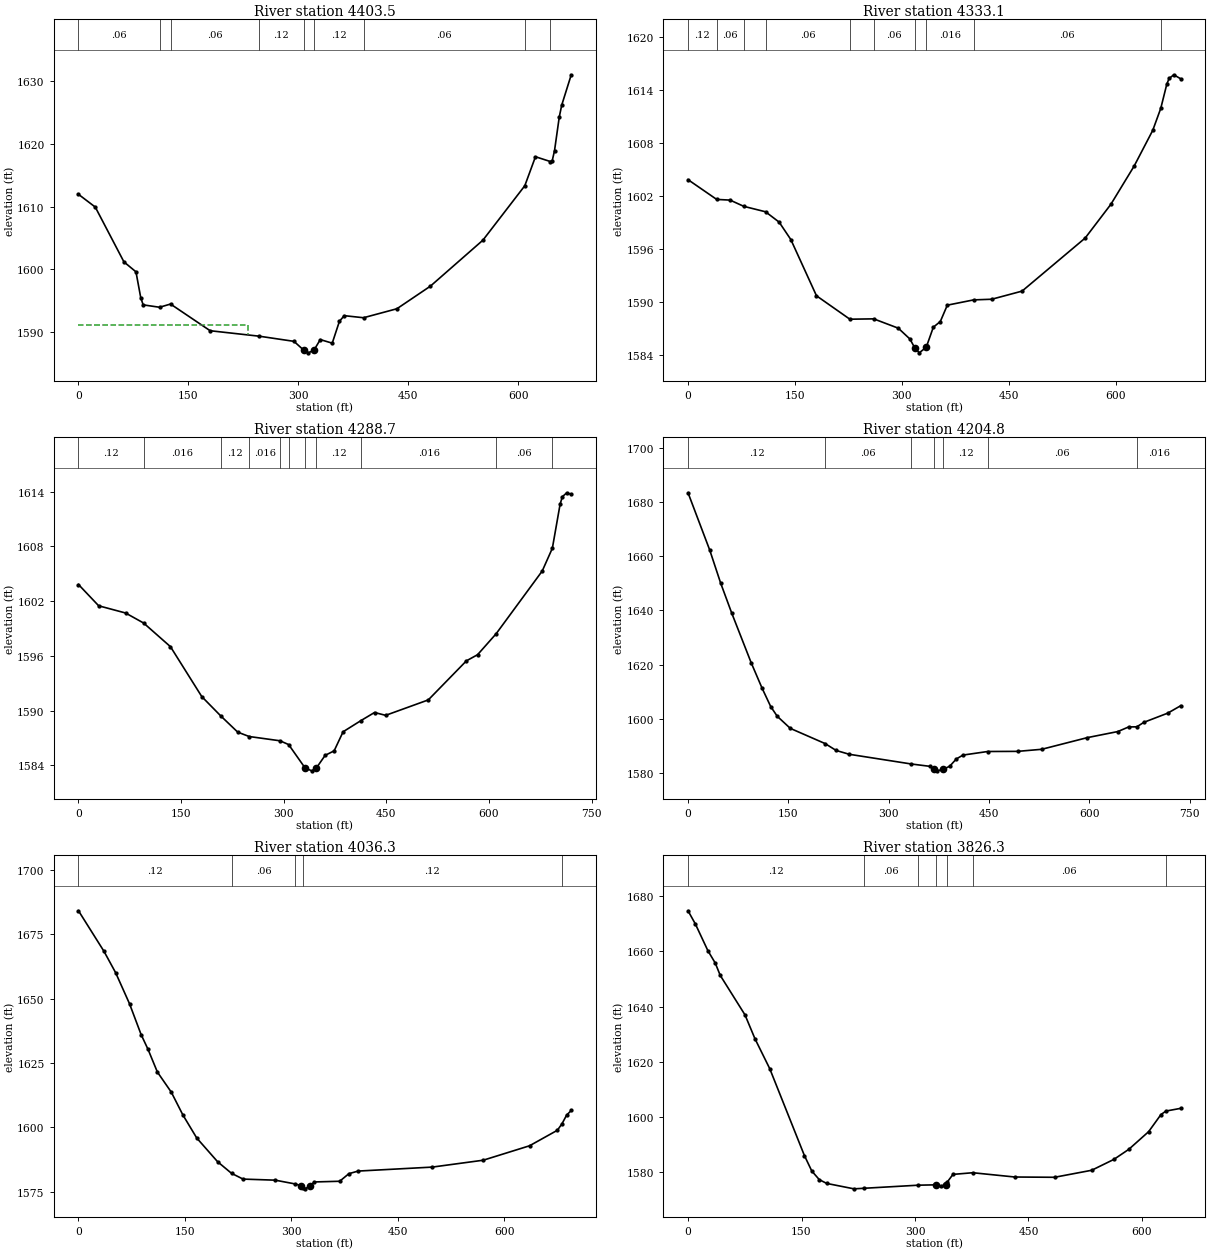
Type RM Length L Ch R = 1 ,4403.5  ,68.9,70.4,71.7
XS GIS Cut Line= 3
     2065122.679      269524.713     2064657.401      269406.658
     2064469.901      269448.325
#Sta/Elev= 30
       0 1611.96    22.9 1609.93      62  1601.2    78.4 1599.62    84.9 1595.51
    88.2 1594.36  110.621593.979  125.54 1594.49   179.6 1590.24   246.51589.371
   293.9 1588.55     307 1587.17   313.5 1586.72   321.2 1587.15   329.8 1588.83
   346.1 1588.26   355.9 1591.74   362.5 1592.64  388.76 1592.31   434.3 1593.74
     480 1597.34   551.6 1604.66  608.761613.329   623.3 1617.95  643.73 1617.18
     646 1617.23   649.3 1618.92   655.8  1624.3   659.1 1626.16   672.1    1631
#Mann= 9 ,-1 , 0
       0     .06       0  110.62     .08       0  125.54     .06       0
   246.5     .12       0     307    .045       0   321.2     .12       0
  388.76     .06       0  608.76    .016       0  643.73     .12       0
#XS Ineff= 2 , 0
          231.17 1591.15
Permanent Ineff=
       F       F
Bank Sta=307,321.2
XS Rating Curve= 0 ,0
Exp/Cntr=0.3,0.1

Type RM Length L Ch R = 1 ,4333.1  ,44.9,44.4,44.1
XS GIS Cut Line= 3
     2065131.537      269471.976     2064598.051      269311.572
     2064471.637      269356.311
#Sta/Elev= 30
       0 1603.88   40.211601.647      59 1601.57   78.231600.864  108.71 1600.25
   127.8 1599.08   144.2 1597.11   180.2 1590.75  227.011588.103  260.421588.142
   294.9 1587.09   311.3 1585.86   317.9 1584.88   324.4  1584.3   334.2 1584.94
   344.1  1587.2   353.9 1587.84   363.7 1589.69  400.641590.287     426 1590.36
   468.6 1591.28   557.1 1597.28   593.1 1601.09   625.8 1605.42   651.9 1609.46
  663.151611.948   671.6 1614.68   674.8 1615.32   681.4 1615.74   691.2 1615.28
#Mann= 10 ,-1 , 0
       0     .12       0   40.21     .06       0   78.23     .08       0
  108.71     .06       0  227.01    .016       0  260.42     .06       0
   317.9    .045       0   334.2    .016       0  400.64     .06       0
  663.15    .016       0
Bank Sta=317.9,334.2
XS Rating Curve= 0 ,0
Exp/Cntr=0.3,0.1

Type RM Length L Ch R = 1 ,4288.7  ,84.2,83.9,83.4
XS GIS Cut Line= 3
     2065147.162      269432.045     2064613.676      269271.642
     2064457.052      269316.985
#Sta/Elev= 30
       0 1603.81    29.5 1601.48    68.8 1600.69   95.171599.592   134.4    1597
   180.2 1591.53   207.91589.417   232.7 1587.64  249.42 1587.16  294.581586.691
  307.111586.276     331 1583.73   340.8  1583.4   347.4 1583.69   360.5  1585.1
   373.6 1585.59   386.7 1587.68  412.931588.911   432.6 1589.79   448.9 1589.48
   511.2 1591.17   566.9 1595.45   583.2 1596.12  610.291598.413   677.7 1605.29
  692.511607.786   703.8  1612.6   707.1 1613.43   713.6 1613.86   720.1 1613.68
#Mann= 11 ,-1 , 0
       0     .12       0   95.17    .016       0   207.9     .12       0
  249.42    .016       0  294.58     .06       0  307.11     .12       0
     331    .045       0   347.4     .12       0  412.93    .016       0
  610.29     .06       0  692.51    .016       0
Bank Sta=331,347.4
XS Rating Curve= 0 ,0
Exp/Cntr=0.3,0.1

Type RM Length L Ch R = 1 ,4204.8  ,165.4,168.5,171.4
XS GIS Cut Line= 4
     2065183.443      269257.352     2065018.512        269307.7
     2064653.929      269203.533     2064476.846      269257.352
#Sta/Elev= 30
       0  1683.4    32.5 1662.21    48.8 1650.04    65.1 1639.13    94.4 1620.66
   110.6 1611.32   123.6 1604.48   133.4 1600.88   152.9 1596.42   204.9 1590.81
   221.5 1588.26   241.1 1586.85  334.081583.258     362 1582.39  368.021581.353
   371.8 1580.74   381.6 1581.27   391.4 1582.49   401.2 1585.14   411.1 1586.56
  447.961587.878   492.8 1587.93   528.7 1588.69   597.1 1593.01   642.5 1595.24
   658.8 1596.95  671.021596.992   681.5 1598.65   717.2 1602.04   736.7  1604.8
#Mann= 7 ,-1 , 0
       0     .12       0   204.9     .06       0  334.08     .12       0
  368.02    .045       0   381.6     .12       0  447.96     .06       0
  671.02    .016       0
Bank Sta=368.02,381.6
XS Rating Curve= 0 ,0
Exp/Cntr=0.3,0.1

Type RM Length L Ch R = 1 ,4036.3  ,213.6,210,204
XS GIS Cut Line= 4
     2065178.679       269172.59      2064972.95      269135.264
     2064797.603      269058.875       2064504.2      269044.986
#Sta/Elev= 30
       0 1684.02    35.9  1668.3    52.3 1660.02    71.9 1647.96    88.2 1636.02
      98 1630.26   111.1  1621.5   130.7  1613.7     147 1604.87   166.6  1595.9
     196  1586.7   215.6 1582.21   231.8 1579.98   277.2 1579.56   305.31578.091
   312.8 1577.46   316.1 1576.64   319.3  1576.2   325.8 1577.34   332.3 1578.87
   367.9 1579.14   380.9 1582.08   393.9 1583.09   498.3 1584.63   570.1  1587.3
   635.3 1592.89   674.5  1598.9     681 1601.39   687.6 1604.79   694.1 1606.59
#Mann= 5 ,-1 , 0
       0     .12       0   215.6     .06       0   305.3    .045       0
   316.1     .12       0     681    .016       0
Bank Sta=312.8,325.8
XS Rating Curve= 0 ,0
Exp/Cntr=0.3,0.1

Type RM Length L Ch R = 1 ,3826.3  ,278.5,262.4,244.9
XS GIS Cut Line= 2
     2065208.205      268987.854     2064569.921      268858.266
#Sta/Elev= 30
       0 1674.72     9.8 1669.89    26.2  1660.3      36 1655.79    42.6 1651.32
    75.3 1637.04    88.4 1628.45     108 1617.58   153.8 1586.14   163.6 1580.52
   173.5 1577.41   183.3 1576.04   219.3 1574.08   232.4 1574.28   304.4  1575.4
   327.6 1575.53   333.8 1574.99   340.4 1575.65   342.6 1576.52   350.2 1579.31
   376.4 1579.91     432 1578.36   484.4 1578.26   533.5  1580.8   562.9 1584.74
   582.6 1588.38   608.8 1594.77   625.1 1600.96   631.7 1602.23   651.3 1603.22
#Mann= 7 ,-1 , 0
       0     .12       0   232.4     .06       0   304.4     .12       0
   327.6    .045       0   342.6     .12       0   376.4     .06       0
   631.7    .016       0
Bank Sta=327.6,340.4
XS Rating Curve= 0 ,0
Exp/Cntr=0.3,0.1

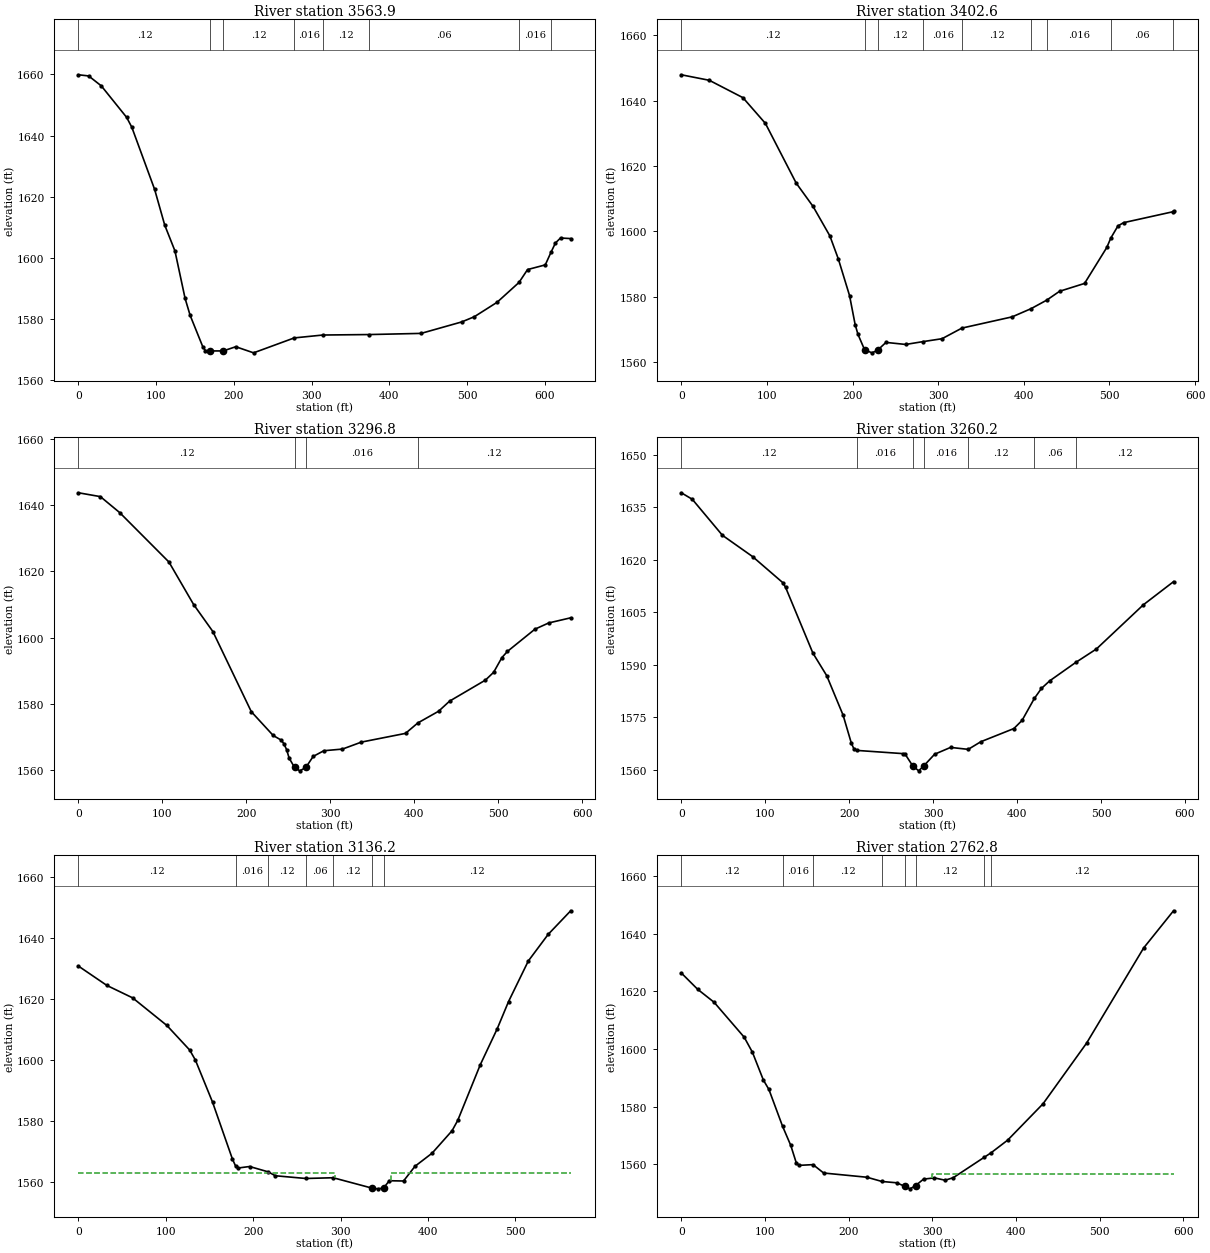
Type RM Length L Ch R = 1 ,3563.9  ,160.7,161.3,161.4
XS GIS Cut Line= 3
     2065152.193       268628.88     2064824.068      268818.116
     2064570.596      268795.547
#Sta/Elev= 30
       0  1659.9    13.1 1659.52    29.4 1656.26      62 1645.94    68.6 1642.74
      98 1622.34     111 1610.64   124.1 1602.22   137.2 1586.62   143.7 1581.07
     160 1570.77   163.3 1569.55   169.8 1569.44   186.1 1569.43   202.4 1570.81
   225.3 1568.81  277.621573.701  314.511574.646  374.251574.801   440.8 1575.18
     493 1578.93   509.3 1580.64   538.6 1585.37  566.821591.879   577.8 1596.09
   600.6 1597.62  607.971601.757   613.7 1604.81   620.2 1606.43   633.3 1606.24
#Mann= 8 ,-1 , 0
       0     .12       0   169.8    .045       0   186.1     .12       0
  277.62    .016       0  314.51     .12       0  374.25     .06       0
  566.82    .016       0  607.97     .06       0
Bank Sta=169.8,186.1
XS Rating Curve= 0 ,0
Exp/Cntr=0.3,0.1

Type RM Length L Ch R = 1 ,3402.6  ,117.6,105.8,93.7
XS GIS Cut Line= 3
     2065094.901      268483.047     2064745.943      268677.491
     2064570.596      268677.491
#Sta/Elev= 30
       0 1647.96    32.7 1646.27      72 1640.94    98.2 1633.07   134.2 1614.75
   153.9  1607.6   173.5 1598.58   183.4  1591.5   196.5 1580.27     203 1571.42
   206.3 1568.41  214.111563.649   222.7 1562.74   229.2 1563.54     239 1565.94
     262 1565.31  282.561566.191   304.5 1567.07  327.711570.327   386.4 1573.77
  408.46 1576.28  426.581578.866   441.7  1581.6   470.9 1584.01   496.9 1595.04
   501.5 1597.89   509.9 1601.63   516.4 1602.63  574.431606.001   574.8 1606.11
#Mann= 9 ,-1 , 0
       0     .12       0  214.11    .045       0   229.2     .12       0
  282.56    .016       0  327.71     .12       0  408.46     .06       0
  426.58    .016       0   501.5     .06       0  574.43     .12       0
Bank Sta=214.11,229.2
XS Rating Curve= 0 ,0
Exp/Cntr=0.3,0.1

Type RM Length L Ch R = 1 ,3296.8  ,36.6,36.6,36.6
XS GIS Cut Line= 4
     2065082.396      268453.008      2064852.04      268480.608
     2064805.145      268559.775     2064558.795      268650.238
#Sta/Elev= 30
       0 1643.74    26.1 1642.58      49 1637.78   107.8 1622.83   137.2    1610
   160.1 1601.85   205.9 1577.65     232 1570.46   241.5 1569.07   244.7 1567.99
   247.9 1566.23     251 1563.62   257.41560.828   263.7 1559.79  270.921560.824
   279.6 1564.14   292.3 1565.86   314.5 1566.36   337.1 1568.47   389.6  1571.1
  404.241574.241     429 1577.78   442.1 1580.83   484.8 1587.18   494.6 1589.54
   504.4 1593.97     511 1595.84   543.8 1602.56   560.2 1604.44   586.4 1605.99
#Mann= 4 ,-1 , 0
       0     .12       0   257.4    .045       0  270.92    .016       0
  404.24     .12       0
Bank Sta=257.4,270.92
XS Rating Curve= 0 ,0
Exp/Cntr=0.3,0.1

Type RM Length L Ch R = 1 ,3260.2  ,106.9,123.9,142.4
XS GIS Cut Line= 4
     2065061.563       268416.55     2064831.207       268444.15
     2064784.311      268523.316     2064537.962       268613.78
#Sta/Elev= 30
       0  1639.2    13.1 1637.34      49 1627.04      85 1620.94   120.9  1613.5
   124.2 1612.18   156.8 1593.34   173.2 1586.92   192.8 1575.58   202.6 1567.58
   205.9 1565.83  209.061565.524   263.7 1564.61   266.9 1564.36   275.51561.185
   282.8 1559.68   289.1 1561.16   301.8 1564.43   320.8 1566.38  341.821565.823
   356.8    1568   396.2 1571.77     406 1574.11  420.551580.368     429 1583.23
   438.8  1585.4  469.841590.668   494.6 1594.54   550.4 1607.15   586.4 1613.78
#Mann= 7 ,-1 , 0
       0     .12       0  209.06    .016       0   275.5    .045       0
   289.1    .016       0  341.82     .12       0  420.55     .06       0
  469.84     .12       0
Bank Sta=275.5,289.1
XS Rating Curve= 0 ,0
Exp/Cntr=0.3,0.1

Type RM Length L Ch R = 1 ,3136.2  ,355.4,373.4,385.9
XS GIS Cut Line= 3
     2065048.026      268337.213     2064633.096      268425.755
     2064494.207      268418.811
#Sta/Elev= 30
       0 1630.73    32.6  1624.4      62 1620.35   101.2 1611.32   127.3 1603.29
   133.8 1600.02   153.4 1586.29   176.2 1567.65  179.741565.425   182.8 1564.73
   195.8 1565.22  217.19 1563.47   225.2  1562.2  260.191561.305  291.44 1561.55
   336.2 1558.13   342.7 1557.92   349.2  1558.2   355.7 1560.57     372 1560.48
   385.1 1565.29   404.7 1569.58   427.5  1576.9     434 1580.27   459.8 1598.47
   479.2 1610.24   492.2 1619.16   514.8 1632.41   537.5  1641.1   563.3 1648.82
#Mann= 7 ,-1 , 0
       0     .12       0  179.74    .016       0  217.19     .12       0
  260.19     .06       0  291.44     .12       0   336.2    .045       0
   349.2     .12       0
#XS Ineff= 2 , 0
          293.62 1563.11  358.12         1563.11
Permanent Ineff=
       F       F
Bank Sta=336.2,349.2
XS Rating Curve= 0 ,0
Exp/Cntr=0.3,0.1

Type RM Length L Ch R = 1 ,2762.8  ,526.6,483.9,438.6
XS GIS Cut Line= 4
     2064973.373      268132.352      2064787.61      268116.727
     2064673.026        268057.7     2064454.276      268220.894
#Sta/Elev= 30
       0 1626.42    19.6 1620.75    39.2 1616.26    75.2 1604.13      85 1598.92
    98.1 1589.27   104.7 1586.02  121.071573.213   130.8 1566.63   137.4 1560.57
   140.6 1559.69  157.431559.945   170.1 1557.04   221.9 1555.57  239.751554.105
   257.3 1553.65     267 1552.43   273.4 1551.55   279.9 1552.67   289.5 1554.92
   302.4 1555.35   315.3 1554.54   325.1 1555.43  362.211562.531  370.291564.072
     390 1568.44   432.3 1581.06   484.3 1602.08   552.5 1635.09   588.2 1647.99
#Mann= 8 ,-1 , 0
       0     .12       0  121.07    .016       0  157.43     .12       0
  239.75     .06       0     267    .045       0   279.9     .12       0
  362.21     .06       0  370.29     .12       0
#XS Ineff= 2 , 0
                          300.08         1556.59
Permanent Ineff=
       F       F
Bank Sta=267,279.9
XS Rating Curve= 0 ,0
Exp/Cntr=0.3,0.1

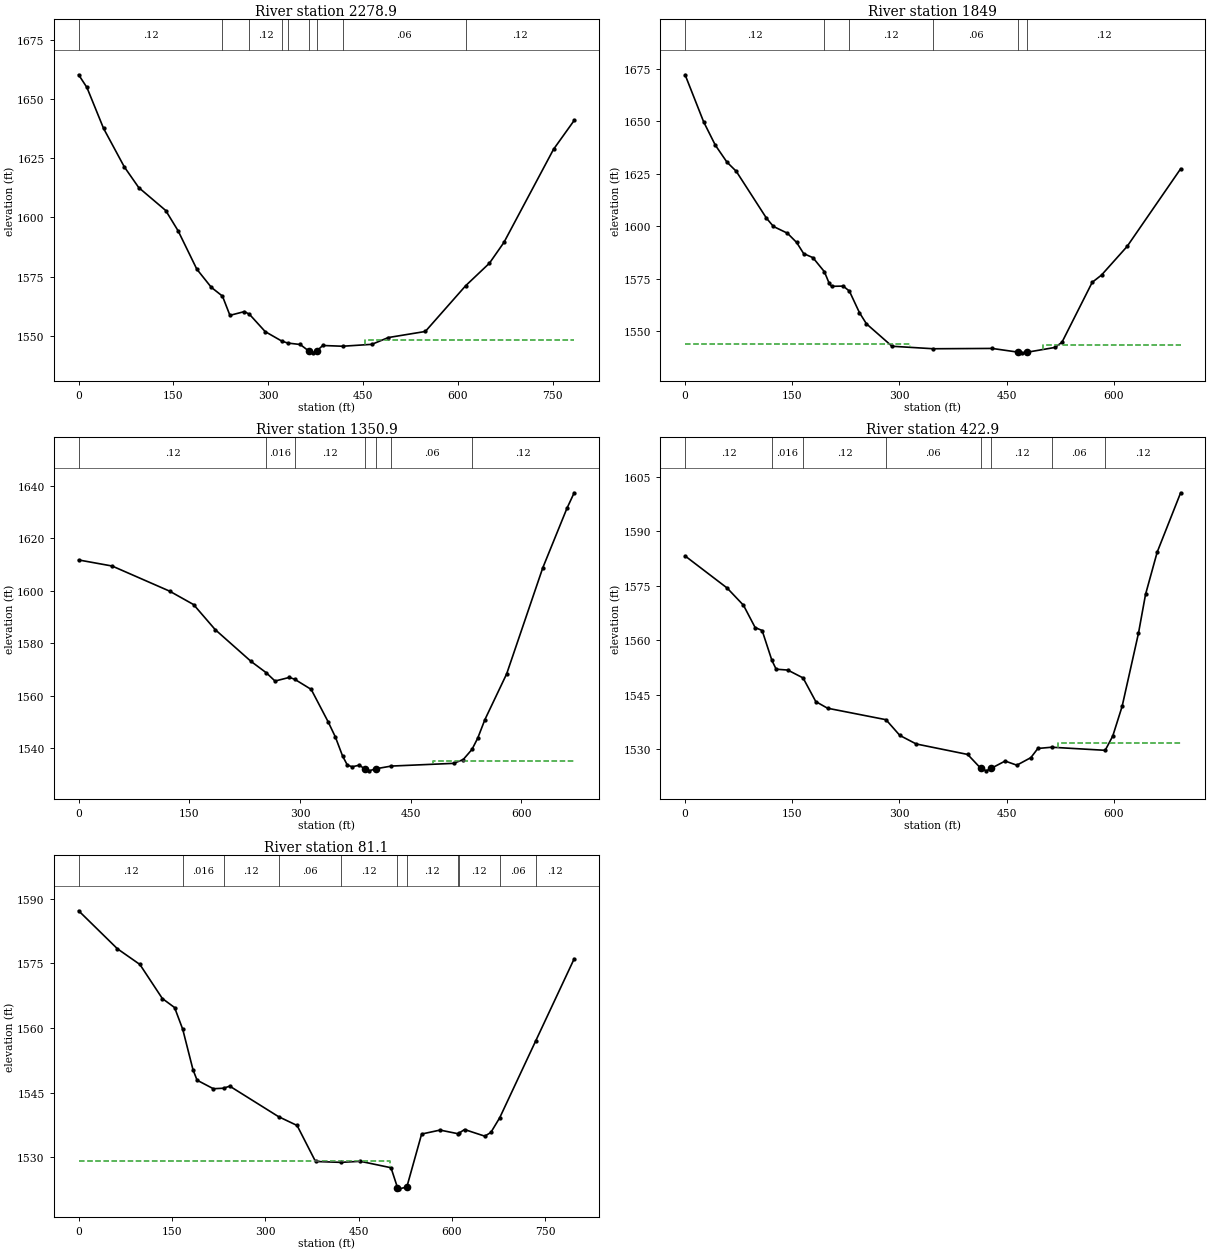
Type RM Length L Ch R = 1 ,2278.9  ,397.1,429.9,455.3
XS GIS Cut Line= 4
     2064839.693      267608.047     2064542.818      267731.311
     2064508.096      267929.227     2064395.248      268165.338
#Sta/Elev= 30
       0 1660.18    13.1 1654.83    39.4 1637.58    72.2 1621.35    95.1 1612.58
   137.8 1602.91   157.4 1594.34     187 1578.16   209.9  1570.5   227.61566.774
   239.4 1558.67   262.4 1560.26  270.321559.105   295.2 1551.81  321.641547.776
  330.881546.982   350.6 1546.37     364 1543.66   370.1 1542.85   376.5 1543.59
   386.3 1545.95  417.731545.635     464 1546.44     490  1549.3   548.6 1551.87
  612.341571.153     650 1580.67   672.9 1589.42   751.4 1628.72   784.1 1640.91
#Mann= 9 ,-1 , 0
       0     .12       0   227.6    .016       0  270.32     .12       0
  321.64     .06       0  330.88     .12       0     364    .045       0
   376.5     .12       0  417.73     .06       0  612.34     .12       0
#XS Ineff= 2 , 0
                          453.64         1548.23
Permanent Ineff=
       F       F
Bank Sta=364,376.5
XS Rating Curve= 0 ,0
Exp/Cntr=0.3,0.1

Type RM Length L Ch R = 1 ,1849    ,501.4,498.1,490.6
XS GIS Cut Line= 3
     2064799.762      267509.088     2064532.401       267566.38
     2064115.735      267621.936
#Sta/Elev= 30
       0 1672.21      26 1649.75    42.3 1638.68    58.6 1630.58    71.6 1626.23
   113.9 1603.88   123.7 1599.92   143.2 1596.72   156.2  1592.3     166 1586.99
     179 1585.05     1951578.369   201.8 1572.77   205.1  1571.4   221.4  1571.5
  229.991569.135   244.1 1558.85   253.9 1553.53   289.7 1542.84  347.581541.647
   429.8  1541.8   465.7 1540.05   472.2  1539.7   478.7 1539.98   517.8 1542.27
   527.6 1544.71     570 1573.31     583 1576.76   618.8 1590.38   693.8 1627.41
#Mann= 6 ,-1 , 0
       0     .12       0     195    .016       0  229.99     .12       0
  347.58     .06       0   465.7    .045       0   478.7     .12       0
#XS Ineff= 2 , 0
          314.92 1543.86  500.79         1543.55
Permanent Ineff=
       F       F
Bank Sta=465.7,478.7
XS Rating Curve= 0 ,0
Exp/Cntr=0.3,0.1

Type RM Length L Ch R = 1 ,1350.9  ,734.8,928,760.3
XS GIS Cut Line= 3
     2064686.915      267094.158     2064414.346      267094.158
     2064041.082      267234.783
#Sta/Elev= 30
       0 1611.74    45.4 1609.43   123.3 1599.86   155.8 1594.74     185 1585.22
   233.6 1573.11  254.281568.776   266.1 1565.63   285.6 1567.02  292.681566.315
   315.1 1562.45     338 1550.14   347.8 1544.37   357.6  1537.1   364.1 1533.63
   370.6 1532.99   380.5  1533.6   387.4 1532.18   393.5 1531.44   402.4 1532.21
  423.521533.253     508 1534.29     521 1535.72  532.941539.594   540.7 1543.87
   550.5 1550.98   579.9 1568.34   628.9 1608.77   661.6  1631.4   671.4 1637.32
#Mann= 7 ,-1 , 0
       0     .12       0  254.28    .016       0  292.68     .12       0
   387.4    .045       0   402.4     .12       0  423.52     .06       0
  532.94     .12       0
#XS Ineff= 2 , 0
                          480.45         1535.29
Permanent Ineff=
       F       F
Bank Sta=387.4,402.4
XS Rating Curve= 0 ,0
Exp/Cntr=0.3,0.1

Type RM Length L Ch R = 1 ,422.9   ,327.1,341.8,364.3
XS GIS Cut Line= 4
     2064484.596       266786.15     2064176.617      266667.785
     2063993.898      266811.432     2063872.085      266859.698
#Sta/Elev= 30
       0 1583.22    58.8 1574.38    81.7 1569.62      98 1563.48   107.8 1562.66
  121.451554.425   127.4 1551.99   143.7 1551.75  165.091549.579   182.9 1543.05
   199.3 1541.23  281.081538.065   300.5 1533.72   323.4 1531.37   395.4 1528.48
   413.6 1524.68   421.6 1523.96   428.6 1524.68   447.8 1526.66   464.2 1525.52
   483.8  1527.6   493.6 1530.13  512.971530.471  587.83 1529.62   598.4 1533.55
   611.5 1541.72   634.4 1561.91   644.3 1572.63   660.6 1584.28   693.4 1600.64
#Mann= 8 ,-1 , 0
       0     .12       0  121.45    .016       0  165.09     .12       0
  281.08     .06       0   413.6    .045       0   428.6     .12       0
  512.97     .06       0  587.83     .12       0
#XS Ineff= 2 , 0
                          521.85         1531.76
Permanent Ineff=
       F       F
Bank Sta=413.6,428.6
XS Rating Curve= 0 ,0
Exp/Cntr=0.3,0.1

Type RM Length L Ch R = 1 ,81.1    ,85.6,81.1,75.8
XS GIS Cut Line= 3
     2064504.623      266752.144     2063941.278      266517.679
     2063810.179      266649.713
#Sta/Elev= 30
       0  1587.2    62.3 1578.38    98.4 1574.74   134.5 1566.83   154.2 1564.73
  167.261559.687   183.7 1550.33   190.3 1547.87   216.5 1545.89  232.871546.009
   242.8 1546.49   321.21539.405     351 1537.36   380.6    1529  421.231528.798
   452.7 1529.04   501.9 1527.55   512.3 1522.94     515 1522.65   527.3 1523.07
   551.1 1535.37   580.7 1536.29  608.981535.463  610.641535.526     620 1536.42
   652.6 1534.88   662.4 1535.75  676.631539.172  734.36 1556.98   796.2 1576.05
#Mann= 11 ,-1 , 0
       0     .12       0  167.26    .016       0  232.87     .12       0
   321.2     .06       0  421.23     .12       0   512.3    .045       0
   527.3     .12       0  608.98    .016       0  610.64     .12       0
  676.63     .06       0  734.36     .12       0
#XS Ineff= 2 , 0
          499.63 1529.03
Permanent Ineff=
       F       F
Bank Sta=512.3,527.3
XS Rating Curve= 0 ,0
Exp/Cntr=0.3,0.1
LCMann Table=0

Chan Stop Cuts=-1
Use User Specified Reach Order=0
Composite Channel Slope=5